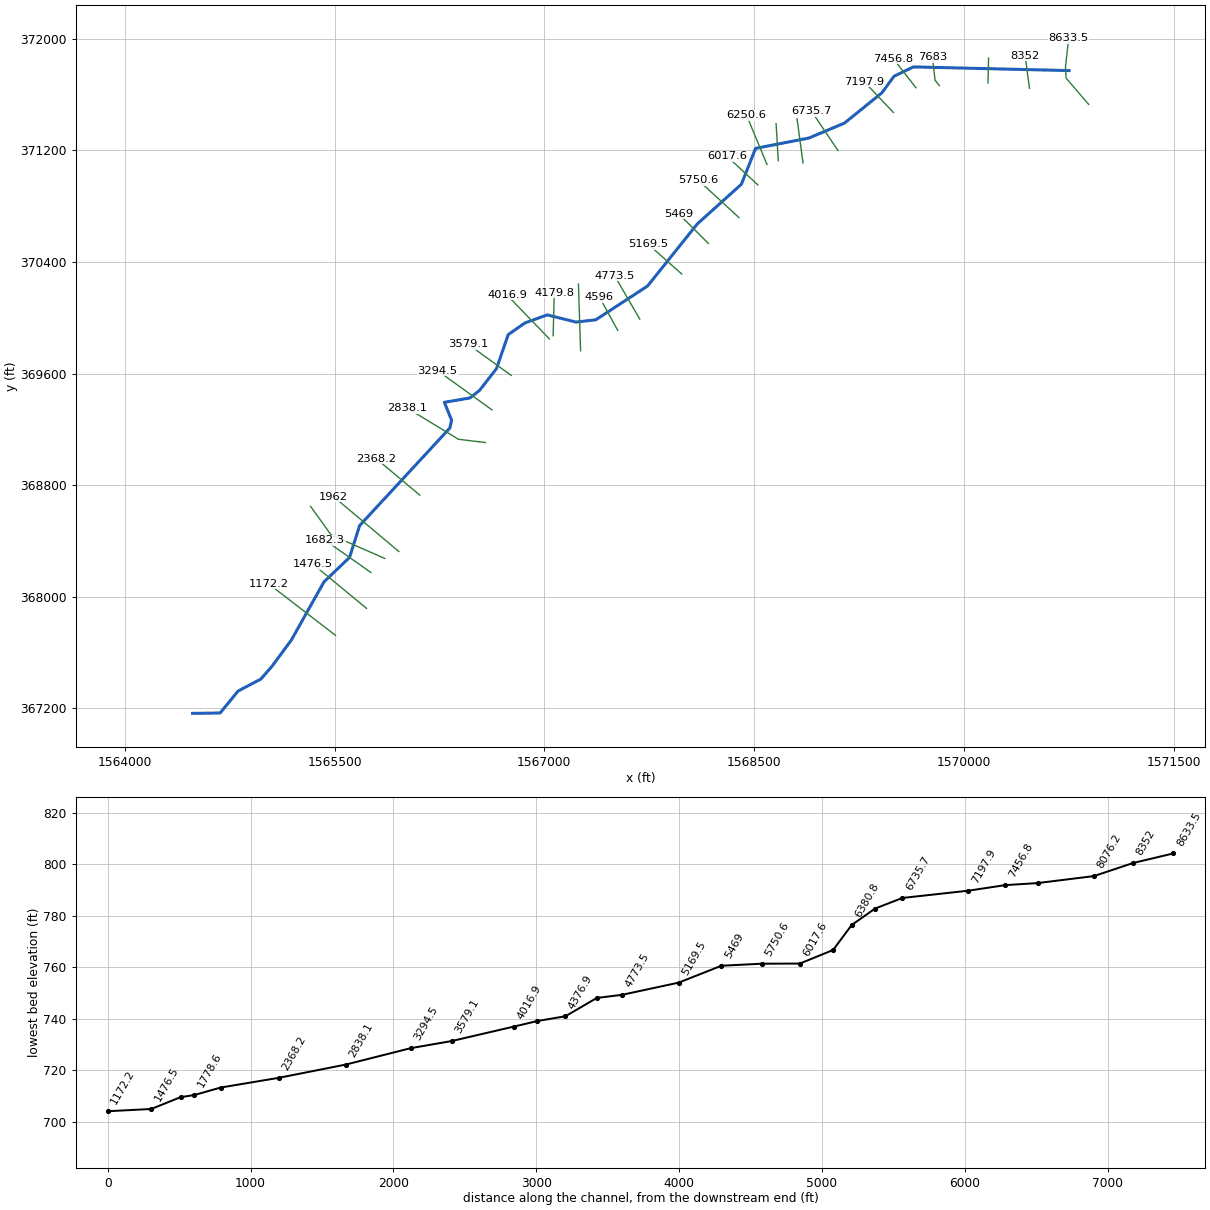
--- MISOURIBR.prj (project) ---

Proj Title=MISOURIBR
Current Plan=p01
Default Exp/Contr=0,0
English Units
Geom File=g01
Flow File=f01
Plan File=p01
BEGIN DESCRIPTION:
END DESCRIPTION:
DSS Export Rating Curves= 0
DSS Export Rating Curve Sorted= 0
DSS Export Volume Flow Curves= 0
DXF OffsetX= 0
DXF OffsetY= 0
DXF ScaleX= 0
DXF ScaleY= 0

--- MISOURIBR.p01 (plan) ---

Plan Title=Floodplain
Program Version=4.00
Geom File=g01
Flow File=f01
K Sum by GR=0
Std Step Tol=0.01
Critical Tol=0.01
Num of Std Step Trials=20
Max Error Tol=0.3
Flow Tol Ratio=0.001
Split Flow NTrial=30
Split Flow Tol=0.02
Split Flow Ratio=0.02
Log Output Level=0
Friction Slope Method=1
Unsteady Friction Slope Method=2
Unsteady Bridges Friction Slope Method=1
Global Log Level=0
CheckData=False
Run HTab=0
Run UNet=0
Run PostProcess=0
UNET Theta=0
UNET Theta Warmup=0
UNET ZTol=0
UNET ZSATol=0
UNET MxIter=0
UNET MaxInSteps=0
UNET DtIC=0
UNET DtMin=0
UNET MaxCRTS=0
UNET WFStab=0
UNET SFStab=0
UNET WFX=0
UNET SFX=0
UNET DSS MLevel=0
UNET DZMax Abort=0
UNET Convert EG Bridges=0
UNET Use Existing IB Tables=0
UNET Froude Limit=0
UNET Froude Power=0
Write IC File=0
Echo Input=False
Echo Output=False
Write Detailed=0

--- MISOURIBR.f01 (steady flow) ---

Flow Title=NFF Regression Equation
Program Version=4.00
Number of Profiles=1
Profile Names=P100yr
River Rch & RM=MISOURIBR,Main      ,8633.5
370.8797
River Rch & RM=MISOURIBR,Main      ,8076.2
376.1227
River Rch & RM=MISOURIBR,Main      ,7456.8
417.2420
River Rch & RM=MISOURIBR,Main      ,6544.6
427.3100
River Rch & RM=MISOURIBR,Main      ,6250.6
502.8953
River Rch & RM=MISOURIBR,Main      ,4179.8
533.4703
River Rch & RM=MISOURIBR,Main      ,1778.6
590.7075
River Rch & RM=MISOURIBR,Main      ,1172.2
663.5688
Boundary for River Rch & Prof#=MISOURIBR,Main      ,1
Up Type=0
Dn Type=3
Dn Slope=0.01125

--- MISOURIBR.g01 (geometry) ---

Geom Title=Geometry
Program Version=4.00

River Reach=MISOURIBR       ,Main
Reach XY= 30
     1570752.537      371770.571     1569639.395      371796.891
     1569501.396      371730.178     1569414.011      371610.879
      1569146.11      371393.914     1568891.083      371286.831
     1568511.087      371213.186     1568409.312       370955.83
     1568094.775      370672.487     1567737.779      370226.242
     1567367.786      369984.491     1567227.015      369968.613
     1567021.398      370020.017     1566861.945      369962.518
      1566741.79      369878.265     1566658.128      369634.427
     1566535.952      369477.591     1566468.366      369424.735
     1566285.535      369393.541     1566337.525        369265.3
     1566324.528      369208.978     1565679.772      368510.609
     1565607.143      368281.729     1565424.655      368106.889
      1565191.46      367690.203     1565051.634       367500.13
     1564972.982      367410.293     1564810.822      367324.832
     1564681.965      367167.257     1564485.258      367164.677

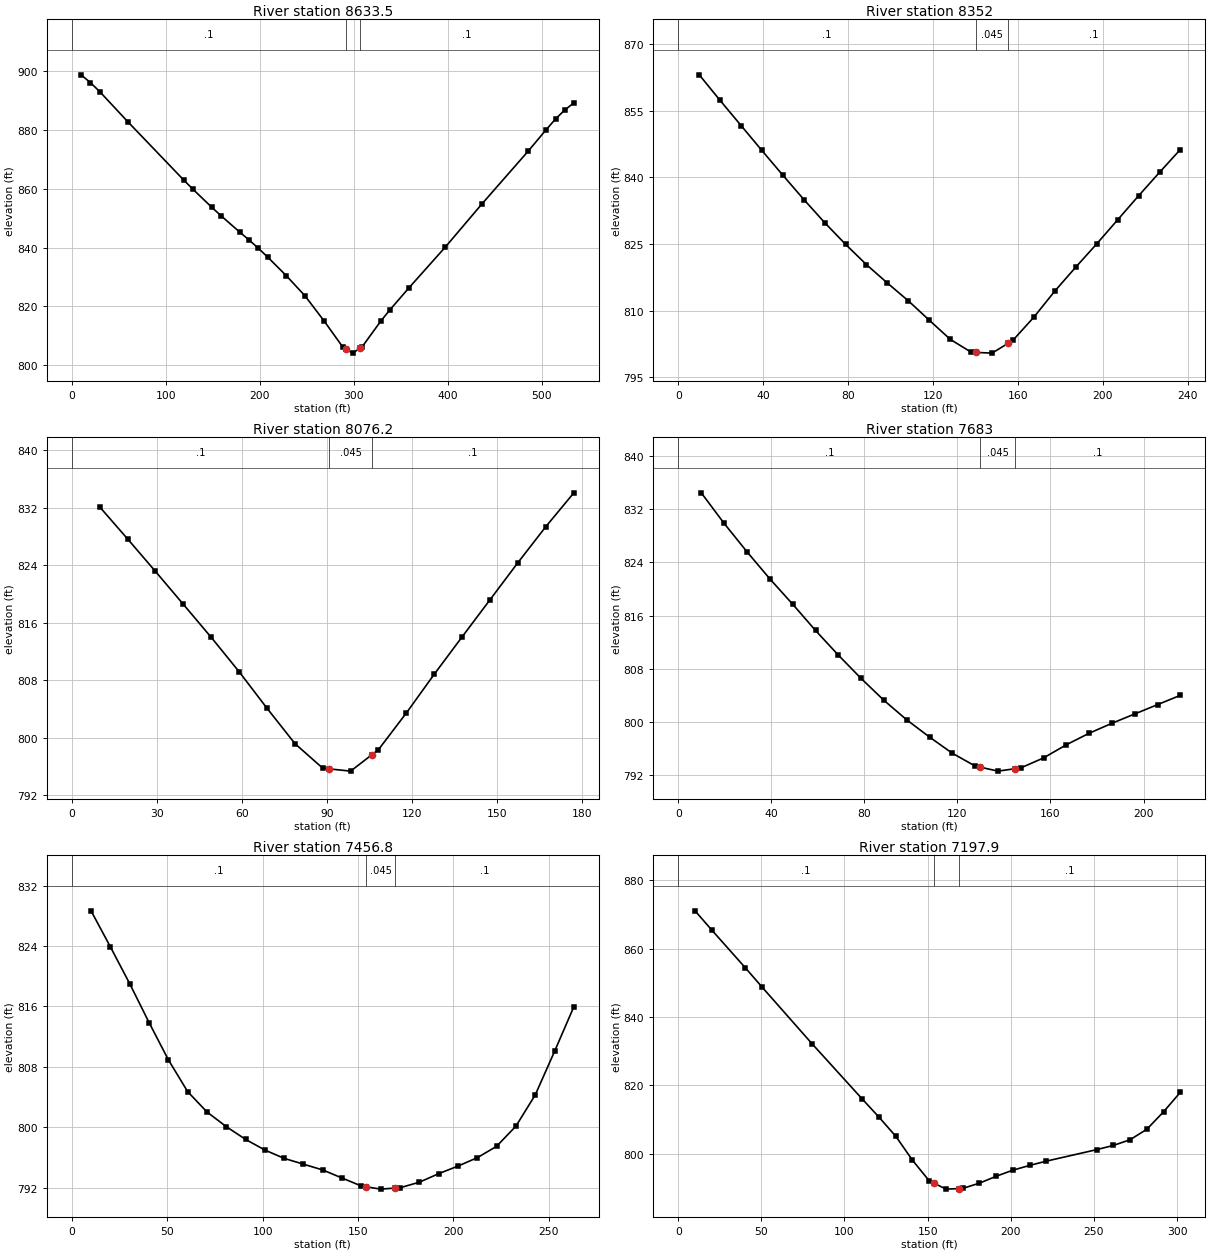
Type RM Length L Ch R = 1 ,8633.5  ,279.5,281.5,283.4
XS GIS Cut Line= 4
     1570892.366      371528.524     1570730.828      371716.985
     1570726.982      371797.754     1570750.059      372001.599
#Sta/Elev= 30
     9.9  898.77    19.9  896.11    29.8  893.04    59.6  882.83   119.1     863
   129.1  859.81   148.9  853.75   158.9  850.83   178.7  845.29   188.6  842.64
   198.6  839.77   208.5  836.78   228.4  830.43   248.2   823.6   268.4  815.11
   288.6   806.1   291.3  805.58   298.8  804.14   306.3  805.72   308.9  806.27
   329.1  815.16   338.8  818.97   358.4  826.21   397.5  840.22   436.5   854.9
   485.4  872.74   504.9  880.17   514.7  883.75   524.5   886.8   534.2  889.23
#Mann= 3 , 0 , 0
       0      .1       0   291.3    .045       0   306.3      .1       0
Bank Sta=291.3,306.3
XS Rating Curve= 0 ,0
Exp/Cntr=0.3,0.1

Type RM Length L Ch R = 1 ,8352    ,279.3,275.8,272.3
XS GIS Cut Line= 2
     1570469.291      371643.908     1570438.522      371878.522
#Sta/Elev= 26
     9.9  863.08    19.7  857.34    29.6  851.67    39.4  846.06    49.3  840.48
    59.2  835.01      69  829.81    78.9   824.9    88.7  820.35    98.6  816.19
   108.5  812.18   118.3  807.84   128.2  803.53     138  800.65   140.4  800.59
   147.9  800.43   155.4  802.63   157.7  803.31   167.6  808.53   177.5  814.42
   187.3  819.77   197.2  825.02     207   830.4   216.9  835.83   226.8  841.12
   236.6  846.26
#Mann= 3 , 0 , 0
       0      .1       0   140.4    .045       0   155.4      .1       0
Bank Sta=140.4,155.4
XS Rating Curve= 0 ,0
Exp/Cntr=0.3,0.1

Type RM Length L Ch R = 1 ,8076.2  ,390.2,393.3,396.4
XS GIS Cut Line= 2
     1570173.139       371682.37     1570176.985      371859.292
#Sta/Elev= 20
     9.8  832.14    19.7  827.65    29.5  823.14    39.3  818.57    49.2  813.94
      59  809.17    68.8   804.1    78.7  799.15    88.5  795.73    90.8  795.64
    98.3  795.33   105.8  797.61   108.1  798.31     118  803.45   127.8  808.83
   137.6  814.02   147.5  819.22   157.3  824.37   167.1  829.36     177  834.08
#Mann= 3 , 0 , 0
       0      .1       0    90.8    .045       0   105.8      .1       0
Bank Sta=90.8,105.8
XS Rating Curve= 0 ,0
Exp/Cntr=0.3,0.1

Type RM Length L Ch R = 1 ,7683    ,213.8,226.1,238.5
XS GIS Cut Line= 3
     1569825.064      371663.139     1569794.295        371701.6
     1569775.064      371866.984
#Sta/Elev= 24
     9.9  834.44    19.7  829.86    29.6  825.56    39.4   821.5    49.3  817.66
      59  813.76    68.8  810.06    78.6  806.55    88.4  803.26    98.2  800.33
     108  797.74   117.8  795.31   127.6  793.39   129.9  793.21   137.4  792.62
   144.9  792.99   147.2   793.1     157   794.6   166.8  796.58   176.6  798.31
   186.4  799.81   196.2  801.21     206  802.61   215.8  804.01
#Mann= 3 , 0 , 0
       0      .1       0   129.9    .045       0   144.9      .1       0
Bank Sta=129.9,144.9
XS Rating Curve= 0 ,0
Exp/Cntr=0.3,0.1

Type RM Length L Ch R = 1 ,7456.8  ,256.8,258.9,261
XS GIS Cut Line= 2
     1569657.758      371647.755      1569496.22      371855.446
#Sta/Elev= 28
    10.1  828.65    20.2   823.9    30.4  818.99    40.5  813.87    50.6  808.95
    60.7  804.74    70.8  802.05      81  800.09    91.1  798.41   101.2     797
   111.3   795.9   121.4  795.13   131.6  794.36   141.7  793.29   151.8  792.24
   154.4  792.13   161.9  791.83   169.4  791.97     172  792.01   182.2  792.75
   192.3  793.88   202.4  794.88   212.5  795.99   222.6  797.49   232.8  800.18
   242.9  804.31     253  810.06   263.1  815.96
#Mann= 3 , 0 , 0
       0      .1       0   154.4    .045       0   169.4      .1       0
Bank Sta=154.4,169.4
XS Rating Curve= 0 ,0
Exp/Cntr=0.3,0.1

Type RM Length L Ch R = 1 ,7197.9  ,465.7,462.2,458.6
XS GIS Cut Line= 2
      1569496.22      371470.833     1569288.529      371690.062
#Sta/Elev= 25
    10.1  871.08    20.1   865.5    40.3  854.45    50.3  848.84    80.5  832.19
   110.7  816.02   120.8   810.7   130.9  805.11   140.9  798.12     151  792.08
   153.6  791.46   161.1  789.67   168.6  789.83   171.1  789.88   181.2  791.42
   191.3  793.44   201.3  795.22   211.4  796.61   221.5  797.87   251.7  801.22
   261.7  802.45   271.8  804.12   281.9   807.2   291.9  812.28     302  817.99
#Mann= 3 , 0 , 0
       0      .1       0   153.6    .045       0   168.6      .1       0
Bank Sta=153.6,168.6
XS Rating Curve= 0 ,0
Exp/Cntr=0.3,0.1

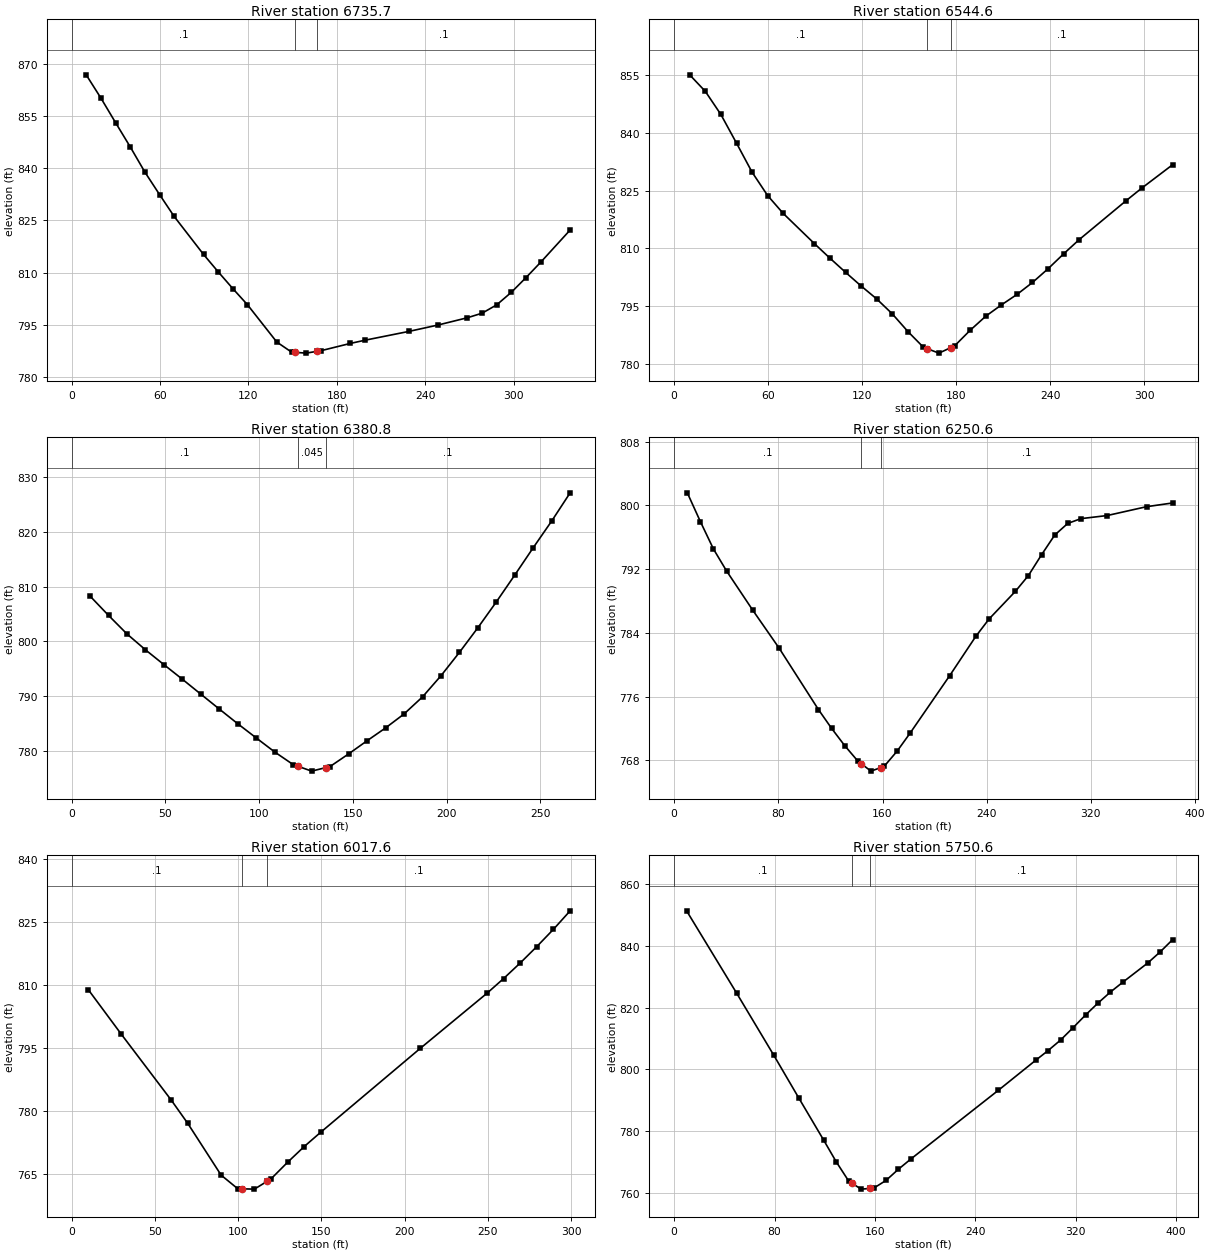
Type RM Length L Ch R = 1 ,6735.7  ,201.6,191.1,180.7
XS GIS Cut Line= 2
     1569100.068      371197.757     1568911.608      371478.525
#Sta/Elev= 28
     9.9  866.82    19.9  860.13    29.8   853.1    39.8   846.1    49.7  838.88
    59.7  832.39    69.6  826.11    89.5  815.21    99.5  810.18   109.4  805.37
   119.3  800.75   139.2  790.03   149.2  787.14   151.6  787.07   159.1  786.84
   166.6  787.36   169.1  787.53     189  789.62   198.9  790.54   228.8  793.08
   248.6  794.92   268.5  797.01   278.5  798.32   288.4  800.72   298.4  804.35
   308.3  808.56   318.3  812.99   338.2  822.22
#Mann= 3 , 0 , 0
       0      .1       0   151.6    .045       0   166.6      .1       0
Bank Sta=151.6,166.6
XS Rating Curve= 0 ,0
Exp/Cntr=0.3,0.1

Type RM Length L Ch R = 1 ,6544.6  ,165.5,163.8,162.1
XS GIS Cut Line= 2
      1568850.07      371109.296     1568807.762      371424.679
#Sta/Elev= 30
     9.9   855.1    19.9  850.79    29.8   844.8    39.8  837.33    49.7   829.8
    59.7  823.68    69.6  819.06    89.5  811.21    99.4  807.43   109.4  803.74
   119.3   800.2   129.3  796.81   139.2  792.95   149.2  788.34   159.1  784.25
   161.5  783.88     169  782.73   176.5  784.15     179  784.62   188.9  788.66
   198.9  792.34   208.8  795.25   218.8  797.99   228.7   801.1   238.7  804.69
   248.6  808.55   258.5  812.24   288.4  822.35   298.3  825.59   318.2  831.74
#Mann= 3 , 0 , 0
       0      .1       0   161.5    .045       0   176.5      .1       0
Bank Sta=161.5,176.5
XS Rating Curve= 0 ,0
Exp/Cntr=0.3,0.1

Type RM Length L Ch R = 1 ,6380.8  ,122.6,130.1,137.7
XS GIS Cut Line= 2
     1568673.148      371124.681     1568657.763      371390.064
#Sta/Elev= 29
     9.8  808.28    19.7  804.74    29.5  801.37    39.4  798.46    49.2  795.77
    59.1  793.09    68.9  790.38    78.8  787.65    88.6  784.98    98.5  782.38
   108.3  779.83   118.1  777.54   120.5  777.25     128  776.34   135.5  776.98
   137.8  777.18   147.7  779.48   157.5  781.87   167.4  784.22   177.2  786.75
   187.1  789.88   196.9  793.72   206.8  798.01   216.6  802.49   226.4  807.18
   236.3  812.11   246.1  817.08     256  821.97   265.8   827.1
#Mann= 3 , 0 , 0
       0      .1       0   120.5    .045       0   135.5      .1       0
Bank Sta=120.5,135.5
XS Rating Curve= 0 ,0
Exp/Cntr=0.3,0.1

Type RM Length L Ch R = 1 ,6250.6  ,223,233,243
XS GIS Cut Line= 2
     1568592.379      371097.758     1568446.226      371451.602
#Sta/Elev= 28
    10.1  801.56    20.1  797.96    30.2   794.5    40.3  791.74    60.4  786.82
    80.6  782.07   110.8  774.36   120.9     772     131  769.83     141  767.91
   143.6  767.58   151.1  766.64   158.6  767.08   161.2  767.23   171.3  769.17
   181.3  771.44   211.6  778.63   231.7  783.57   241.8  785.73   261.9  789.18
     272  791.18   282.1  793.79   292.2  796.26   302.2  797.72   312.3  798.32
   332.5  798.71   362.7  799.82   382.8  800.29
#Mann= 3 , 0 , 0
       0      .1       0   143.6    .045       0   158.6      .1       0
Bank Sta=143.6,158.6
XS Rating Curve= 0 ,0
Exp/Cntr=0.3,0.1

Type RM Length L Ch R = 1 ,6017.6  ,266.9,267.1,267.2
XS GIS Cut Line= 2
     1568526.995      370951.605     1568307.765       371155.45
#Sta/Elev= 20
      10  808.84    29.9   798.2    59.9  782.52    69.8  776.99    89.8   764.7
    99.8  761.46   102.3  761.44   109.8  761.37   117.3   763.2   119.7  763.78
   129.7  767.75   139.7   771.5   149.7  774.93   209.5  794.89   249.5  807.98
   259.4  811.45   269.4  815.16   279.4  819.08   289.4  823.19   299.4  827.58
#Mann= 3 , 0 , 0
       0      .1       0   102.3    .045       0   117.3      .1       0
Bank Sta=102.3,117.3
XS Rating Curve= 0 ,0
Exp/Cntr=0.3,0.1

Type RM Length L Ch R = 1 ,5750.6  ,282.5,281.6,280.7
XS GIS Cut Line= 2
      1568392.38      370716.991     1568100.074       370986.22
#Sta/Elev= 26
     9.9   851.3    49.7  824.75    79.5  804.54    99.3  790.81   119.2  777.14
   129.2  770.14   139.1  763.93   141.5  763.29     149  761.31   156.5  761.53
     159  761.61   168.9  764.13   178.8  767.76   188.8  771.09   258.3  793.23
   288.1  802.95   298.1  806.12     308  809.51   317.9  813.48   327.9   817.6
   337.8  821.45   347.7  825.02   357.7  828.24   377.5  834.43   387.5  838.05
   397.4  842.02
#Mann= 3 , 0 , 0
       0      .1       0   141.5    .045       0   156.5      .1       0
Bank Sta=141.5,156.5
XS Rating Curve= 0 ,0
Exp/Cntr=0.3,0.1

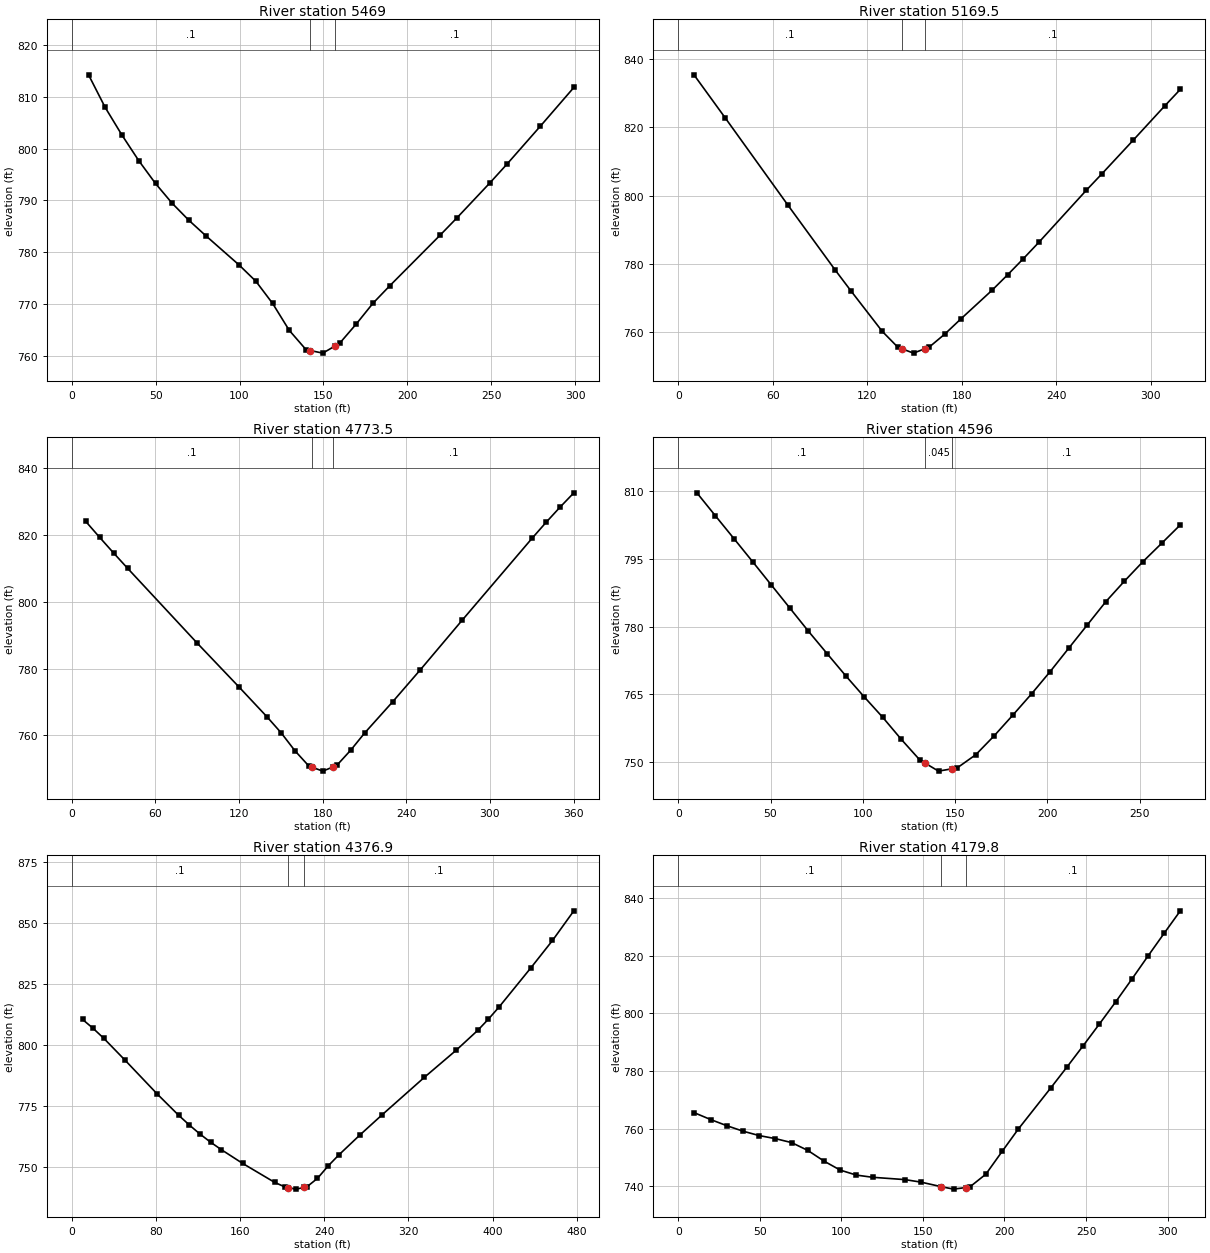
Type RM Length L Ch R = 1 ,5469    ,298.1,299.5,300.8
XS GIS Cut Line= 2
     1568173.151      370532.376     1567961.614      370743.914
#Sta/Elev= 26
      10  814.26    19.9  807.97    29.9  802.63    39.9   797.7    49.9  793.28
    59.8  789.47    69.8  786.17    79.8  783.22    99.7  777.55   109.7  774.41
   119.7  770.12   129.6  764.93   139.6   761.2   142.1  761.03   149.6  760.53
   157.1  761.95   159.6  762.42   169.5  766.14   179.5  770.16   189.5  773.53
   219.4  783.27   229.4   786.6   249.3  793.44   259.3     797   279.2  804.33
   299.2  811.82
#Mann= 3 , 0 , 0
       0      .1       0   142.1    .045       0   157.1      .1       0
Bank Sta=142.1,157.1
XS Rating Curve= 0 ,0
Exp/Cntr=0.3,0.1

Type RM Length L Ch R = 1 ,5169.5  ,403.2,396,388.8
XS GIS Cut Line= 2
     1567982.767      370313.147     1567744.307      370524.684
#Sta/Elev= 22
      10  835.38    29.9  822.74    69.7  797.22    99.6  778.31   109.6  772.21
   129.5  760.35   139.5  755.66   141.9  755.25   149.4  753.96   156.9   755.3
   159.4  755.74   169.3  759.55   179.3   763.9   199.2  772.33   209.2   776.9
   219.2  781.62   229.1  786.44     259  801.55     269  806.41   288.9  816.26
   308.8  826.23   318.8  831.12
#Mann= 3 , 0 , 0
       0      .1       0   141.9    .045       0   156.9      .1       0
Bank Sta=141.9,156.9
XS Rating Curve= 0 ,0
Exp/Cntr=0.3,0.1

Type RM Length L Ch R = 1 ,4773.5  ,178.1,177.5,177
XS GIS Cut Line= 2
     1567682.769      369990.072     1567502.001      370301.609
#Sta/Elev= 23
      10  824.11      20  819.32      30  814.64      40  810.07      90  787.61
   120.1  774.41   140.1   765.5   150.1  760.78   160.1  755.35   170.1  750.76
   172.6  750.38   180.1  749.24   187.6  750.52   190.1  750.95   200.1  755.51
   210.1  760.66   230.1  769.97   250.1  779.63   280.1  794.49   330.2  819.03
   340.2  823.78   350.2  828.33   360.2  832.67
#Mann= 3 , 0 , 0
       0      .1       0   172.6    .045       0   187.6      .1       0
Bank Sta=172.6,187.6
XS Rating Curve= 0 ,0
Exp/Cntr=0.3,0.1

Type RM Length L Ch R = 1 ,4596    ,229.7,219.1,208.5
XS GIS Cut Line= 2
     1567525.078      369909.303     1567394.309      370147.763
#Sta/Elev= 29
    10.1  809.65    20.1  804.58    30.2   799.5    40.3   794.4    50.4  789.25
    60.4  784.16    70.5  779.01    80.6  774.06    90.7  769.15   100.7  764.48
   110.8  759.92   120.9  755.02   130.9  750.47   133.5  749.84     141  748.01
   148.5  748.54   151.1  748.72   161.2  751.65   171.2  755.85   181.3  760.43
   191.4  765.12   201.5  770.06   211.5  775.21   221.6  780.39   231.7  785.57
   241.7  790.08   251.8  794.43   261.9  798.47     272  802.55
#Mann= 3 , 0 , 0
       0      .1       0   133.5    .045       0   148.5      .1       0
Bank Sta=133.5,148.5
XS Rating Curve= 0 ,0
Exp/Cntr=0.3,0.1

Type RM Length L Ch R = 1 ,4376.9  ,198.3,197.1,195.9
XS GIS Cut Line= 2
     1567259.694       369763.15      1567244.31       370240.07
#Sta/Elev= 30
    10.2  810.46    20.3  806.79    30.5  802.68    50.8  793.68    81.2  779.91
   101.5  771.21   111.7  767.21   121.8  763.51     132  760.13   142.1  757.11
   162.4  751.46   192.9  743.67   203.1  741.72   205.7  741.51   213.2  740.92
   220.7   741.6   223.4  741.84   233.5  745.32   243.7  750.43   253.8  754.92
   274.1   763.2   294.4  771.15     335  786.68   365.5  797.88   385.8  805.95
   395.9  810.53   406.1  815.53   436.6  831.72   456.9   842.8   477.2  854.95
#Mann= 3 , 0 , 0
       0      .1       0   205.7    .045       0   220.7      .1       0
Bank Sta=205.7,220.7
XS Rating Curve= 0 ,0
Exp/Cntr=0.3,0.1

Type RM Length L Ch R = 1 ,4179.8  ,143.8,162.9,182
XS GIS Cut Line= 2
     1567063.542      369870.842     1567071.234      370178.532
#Sta/Elev= 30
     9.9  765.54    19.9  763.18    29.8  761.05    39.7  759.15    49.6  757.63
    59.6  756.56    69.5  755.19    79.4  752.49    89.4  748.76    99.3  745.65
   109.2  743.92   119.1  743.16     139  742.35   148.9  741.47   161.3  739.89
   168.8  739.05   176.3   739.6   178.7  739.78   188.6  744.24   198.6  752.16
   208.5   759.9   228.4  774.17   238.3   781.4   248.2  788.76   258.1  796.26
   268.1  803.94     278  811.82   287.9  819.84   297.9  827.81   307.8  835.59
#Mann= 3 , 0 , 0
       0      .1       0   161.3    .045       0   176.3      .1       0
Bank Sta=161.3,176.3
XS Rating Curve= 0 ,0
Exp/Cntr=0.3,0.1

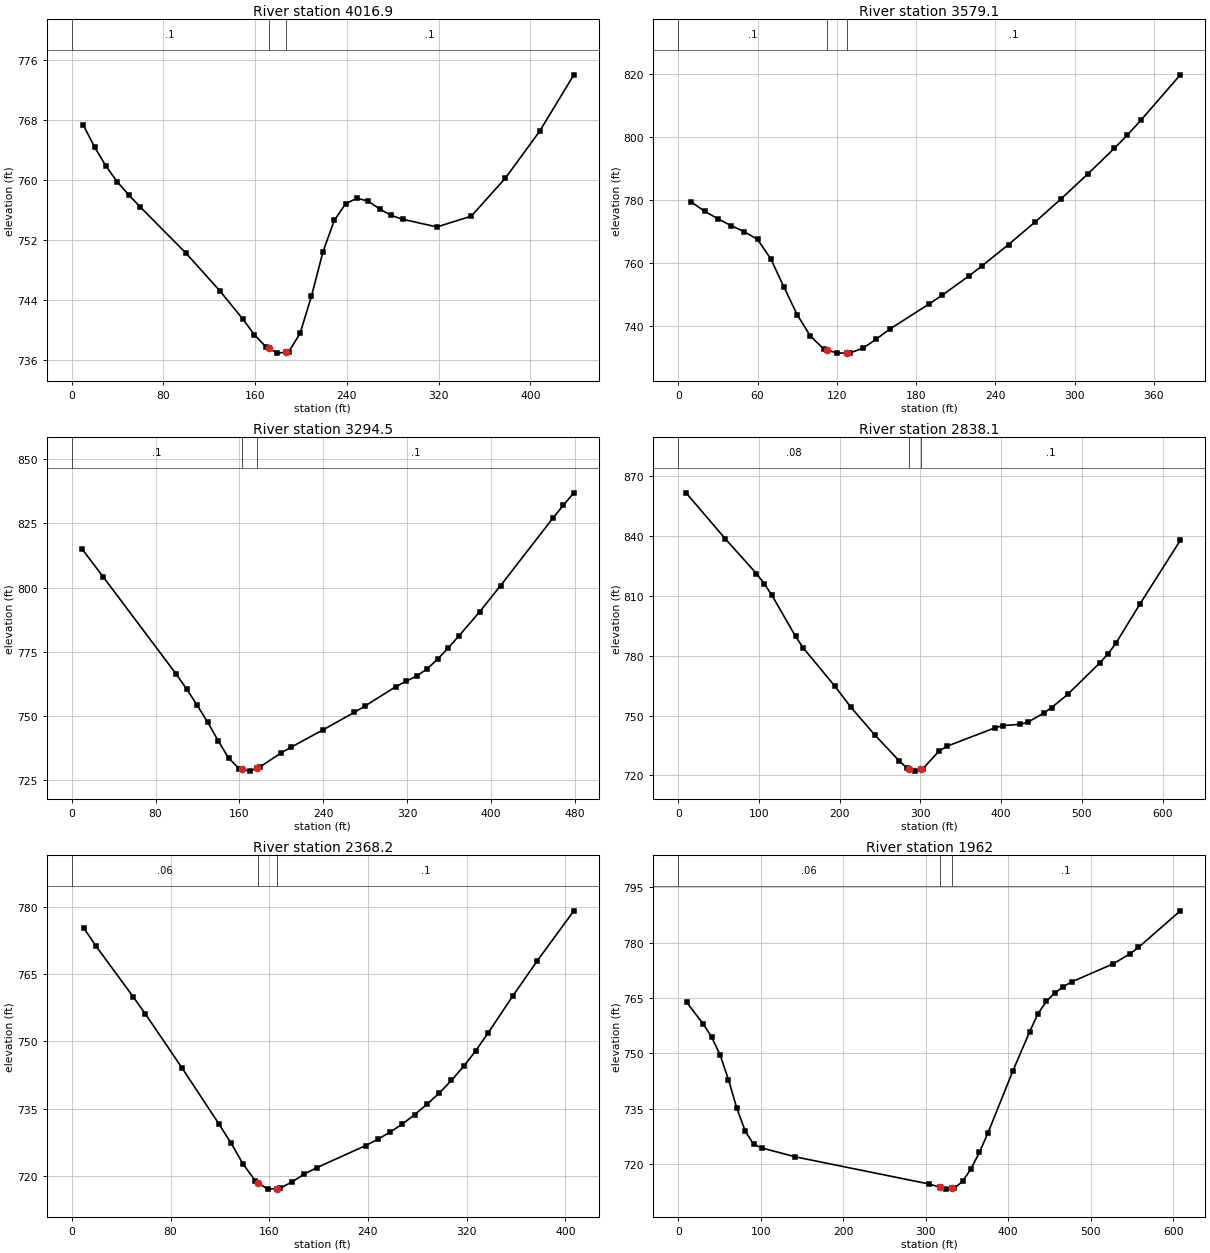
Type RM Length L Ch R = 1 ,4016.9  ,435,437.8,440.6
XS GIS Cut Line= 2
     1567036.619      369847.765     1566732.774      370163.148
#Sta/Elev= 30
      10  767.31    19.9  764.35    29.9  761.81    39.8   759.7    49.8  757.97
    59.7  756.38    99.5  750.25   129.4  745.16   149.3  741.43   159.2  739.36
   169.2  737.77   171.7  737.56   179.2  736.91   186.7  737.02   189.1  737.06
   199.1  739.53     209  744.46     219  750.35   228.9  754.58   238.9  756.81
   248.8  757.55   258.8  757.13   268.7  756.09   278.7  755.25   288.6  754.74
   318.5  753.72   348.4  755.15   378.2  760.22   408.1  766.47   437.9  773.98
#Mann= 3 , 0 , 0
       0      .1       0   171.7    .045       0   186.7      .1       0
Bank Sta=171.7,186.7
XS Rating Curve= 0 ,0
Exp/Cntr=0.3,0.1

Type RM Length L Ch R = 1 ,3579.1  ,284.2,284.6,284.9
XS GIS Cut Line= 2
     1566763.543      369586.228     1566455.853      369809.304
#Sta/Elev= 30
      10   779.3      20  776.38      30  774.01      40  771.82      50   769.9
      60  767.46      70   761.3      80  752.29      90  743.52     100   736.7
     110  732.67   112.5  732.32     120  731.27   127.5  731.32     130  731.34
     140  732.87     150  735.76     160  738.89     190  746.93     200  749.75
     220  755.82     230  759.04     250  765.82     270  772.94     290  780.43
     310  788.26     330  796.38     340  800.67     350  805.28     380  819.79
#Mann= 3 , 0 , 0
       0      .1       0   112.5    .045       0   127.5      .1       0
Bank Sta=112.5,127.5
XS Rating Curve= 0 ,0
Exp/Cntr=0.3,0.1

Type RM Length L Ch R = 1 ,3294.5  ,453.2,456.4,459
XS GIS Cut Line= 2
     1566625.083      369340.076     1566236.624      369620.843
#Sta/Elev= 30
      10  814.94      30  804.19    99.9   766.2   109.8  760.41   119.8  754.14
   129.8  747.52   139.8  740.37   149.8  733.57   159.8  729.53   162.3  729.28
   169.8  728.53   177.3  729.78   179.7  730.18   199.7  735.57   209.7  737.92
   239.7  744.57   269.6  751.39   279.6   753.8   309.5  761.47   319.5  763.61
   329.5  765.58   339.5  768.46   349.5  772.24   359.5  776.58   369.5  781.13
   389.4   790.6   409.4   800.8   459.3  827.07   469.3   832.1   479.3  836.92
#Mann= 3 , 0 , 0
       0      .1       0   162.3    .045       0   177.3      .1       0
Bank Sta=162.3,177.3
XS Rating Curve= 0 ,0
Exp/Cntr=0.3,0.1

Type RM Length L Ch R = 1 ,2838.1  ,473.3,469.9,466.5
XS GIS Cut Line= 3
     1566578.929      369105.462     1566386.623      369128.538
      1566021.24      369351.614
#Sta/Elev= 30
     9.7  861.61    58.1  838.65    96.8  821.17   106.5  816.06   116.2  810.18
   145.3  789.65   154.9  783.83   193.7  764.86   213.6  754.27   243.5  740.24
   273.3  727.44   283.3  723.62   285.7  723.26   293.2  722.14   300.7  723.12
   303.2  723.45   323.1  732.25   333.1  734.66   392.8  743.93   402.8  744.98
   422.7  745.59   432.6  746.59   452.5  751.16   462.5  754.02   482.4  760.62
   522.2  776.42   532.2  780.85   542.1  786.28     572  806.01   621.8  837.79
#Mann= 3 , 0 , 0
       0     .08       0   285.7    .045       0   300.7      .1       0
Bank Sta=285.7,300.7
XS Rating Curve= 0 ,0
Exp/Cntr=0.3,0.1

Type RM Length L Ch R = 1 ,2368.2  ,406.2,406.2,406.1
XS GIS Cut Line= 2
     1566109.701      368728.541     1565798.164      368990.078
#Sta/Elev= 30
     9.9  775.27    19.8  771.23    49.6  760.03    59.5   756.2    89.3  744.08
   119.1  731.61     129  727.29   138.9  722.57   148.8  718.79   151.2  718.35
   158.7  716.99   166.2  717.12   168.7  717.17   178.6  718.63   188.5  720.37
   198.4  721.77   238.1  726.73     248  728.13   257.9  729.73   267.9  731.54
   277.8  733.63   287.7  735.95   297.6   738.4   307.6  741.29   317.5  744.43
   327.4  747.94   337.3  751.87   357.2  760.09     377  767.95   406.8  779.18
#Mann= 3 , 0 , 0
       0     .06       0   151.2    .045       0   166.2      .1       0
Bank Sta=151.2,166.2
XS Rating Curve= 0 ,0
Exp/Cntr=0.3,0.1

Type RM Length L Ch R = 1 ,1962    ,177,183.4,189.8
XS GIS Cut Line= 2
     1565959.702      368324.697      1565494.32      368717.002
#Sta/Elev= 30
    10.1  763.87    30.4  757.92    40.6  754.37    50.7   749.6    60.9  742.87
      71  735.15    81.2  728.94    91.3  725.37   101.4  724.37     142  721.96
   304.3   714.6   317.1  713.75   324.6  713.22   332.1   713.4   334.8  713.46
   344.9  715.37   355.1  718.78   365.2   723.2   375.3  728.34   405.8  745.29
   426.1  755.88   436.2  760.77   446.4  764.09   456.5  766.35   466.6  768.02
   476.8  769.34   527.5  774.26   547.8  776.97     558  778.69   608.7   788.6
#Mann= 3 , 0 , 0
       0     .06       0   317.1    .045       0   332.1      .1       0
Bank Sta=317.1,332.1
XS Rating Curve= 0 ,0
Exp/Cntr=0.3,0.1

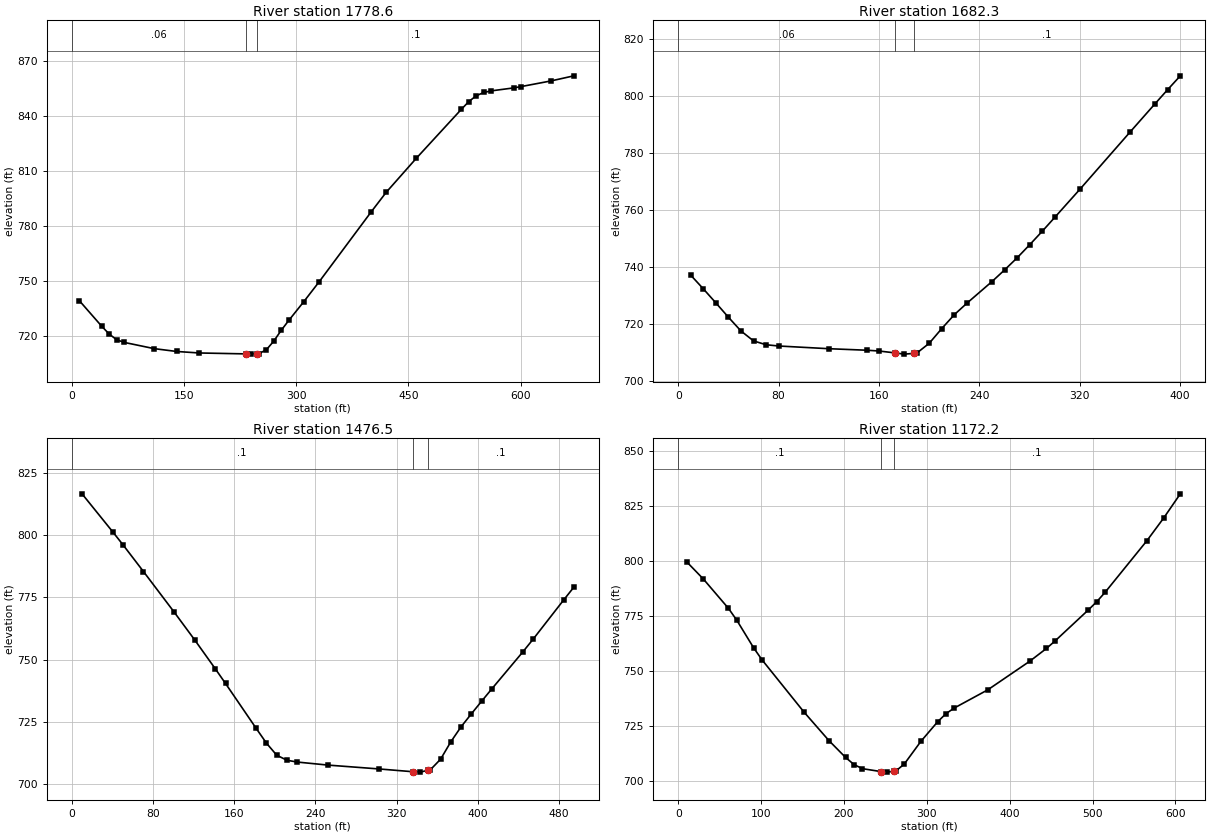
Type RM Length L Ch R = 1 ,1778.6  ,100.9,96.3,91.5
XS GIS Cut Line= 3
     1565859.703      368274.697     1565475.089      368443.927
     1565328.936      368647.772
#Sta/Elev= 30
      10  739.46      40   725.5      50  721.25      60  718.15      70  716.71
   110.1  713.31   140.1  711.77   170.1  710.95   232.6  710.45   240.1  710.32
   247.6  710.52   250.1  710.58   260.1   712.7   270.1  717.48   280.1  723.38
   290.1   728.7   310.1  738.88   330.2  749.47   400.2  787.76   420.2  798.37
   460.3  816.83   520.5  843.48   530.6  847.76   540.6  850.93   550.6   852.7
   560.7  853.59   590.8  855.21   600.8  855.94   640.9  859.03     671  861.77
#Mann= 3 , 0 , 0
       0     .06       0   232.6    .045       0   247.6      .1       0
Bank Sta=232.6,247.6
XS Rating Curve= 0 ,0
Exp/Cntr=0.3,0.1

Type RM Length L Ch R = 1 ,1682.3  ,207.4,205.7,204.2
XS GIS Cut Line= 2
     1565759.703      368174.698     1565432.782      368405.466
#Sta/Elev= 30
      10  737.16      20  732.38      30  727.46      40  722.43      50  717.62
      60  714.14      70  712.79      80  712.35     120   711.4   150.1  710.87
   160.1  710.59   172.6  709.94   180.1   709.5   187.6  709.75   190.1  709.84
   200.1  713.32   210.1  718.48   220.1  723.34   230.1  727.35   250.1  734.94
   260.1     739   270.1  743.24   280.1  747.82   290.1  752.54   300.1  757.42
   320.1  767.25   360.1  787.32   380.2  797.33   390.2  802.25   400.2  807.05
#Mann= 3 , 0 , 0
       0     .06       0   172.6    .045       0   187.6      .1       0
Bank Sta=172.6,187.6
XS Rating Curve= 0 ,0
Exp/Cntr=0.3,0.1

Type RM Length L Ch R = 1 ,1476.5  ,303.5,304.3,305.2
XS GIS Cut Line= 2
     1565728.934      367917.007     1565348.167       368232.39
#Sta/Elev= 29
    10.1  816.46    40.4  801.19    50.5  795.99    70.6  785.31   100.9  769.01
   121.1  757.87   141.3  746.34   151.4  740.44   181.6  722.43   191.7  716.52
   201.8  711.69   211.9  709.66     222  708.94   252.3  707.72   302.7  706.17
   335.6  705.07   343.1   704.9   350.6  705.63   353.2  705.88   363.2  710.09
   373.3  717.08   383.4   723.1   393.5  728.27   403.6  733.33   413.7  738.31
     444  753.01   454.1  758.09   484.3  773.87   494.4  779.04
#Mann= 3 , 0 , 0
       0      .1       0   335.6    .045       0   350.6      .1       0
Bank Sta=335.6,350.6
XS Rating Curve= 0 ,0
Exp/Cntr=0.3,0.1

Type RM Length L Ch R = 1 ,1172.2  ,1192.8,1172.2,1151.7
XS GIS Cut Line= 2
     1565507.033      367723.809     1565027.372      368094.017
#Sta/Elev= 30
    10.1   799.8    30.3  791.94    60.6  778.58    70.7  773.15    90.9  760.67
     101   755.2   151.5  731.49   181.8  718.41     202  710.69   212.1  707.49
   222.2  705.61     245  704.26   252.5  704.03     260  704.43   262.6  704.56
   272.7  707.67   292.9  718.07   313.1  726.97   323.2  730.67   333.3  733.25
   373.6   741.5   424.1  754.48   444.3  760.31   454.4  763.62   494.8  777.82
   504.9  781.54     515  785.82   565.5  809.33   585.7  819.63   605.9  830.71
#Mann= 3 , 0 , 0
       0      .1       0     245    .045       0     260      .1       0
Bank Sta=245,260
XS Rating Curve= 0 ,0
Exp/Cntr=0.3,0.1

Chan Stop Cuts=-1
Use User Specified Reach Order=0